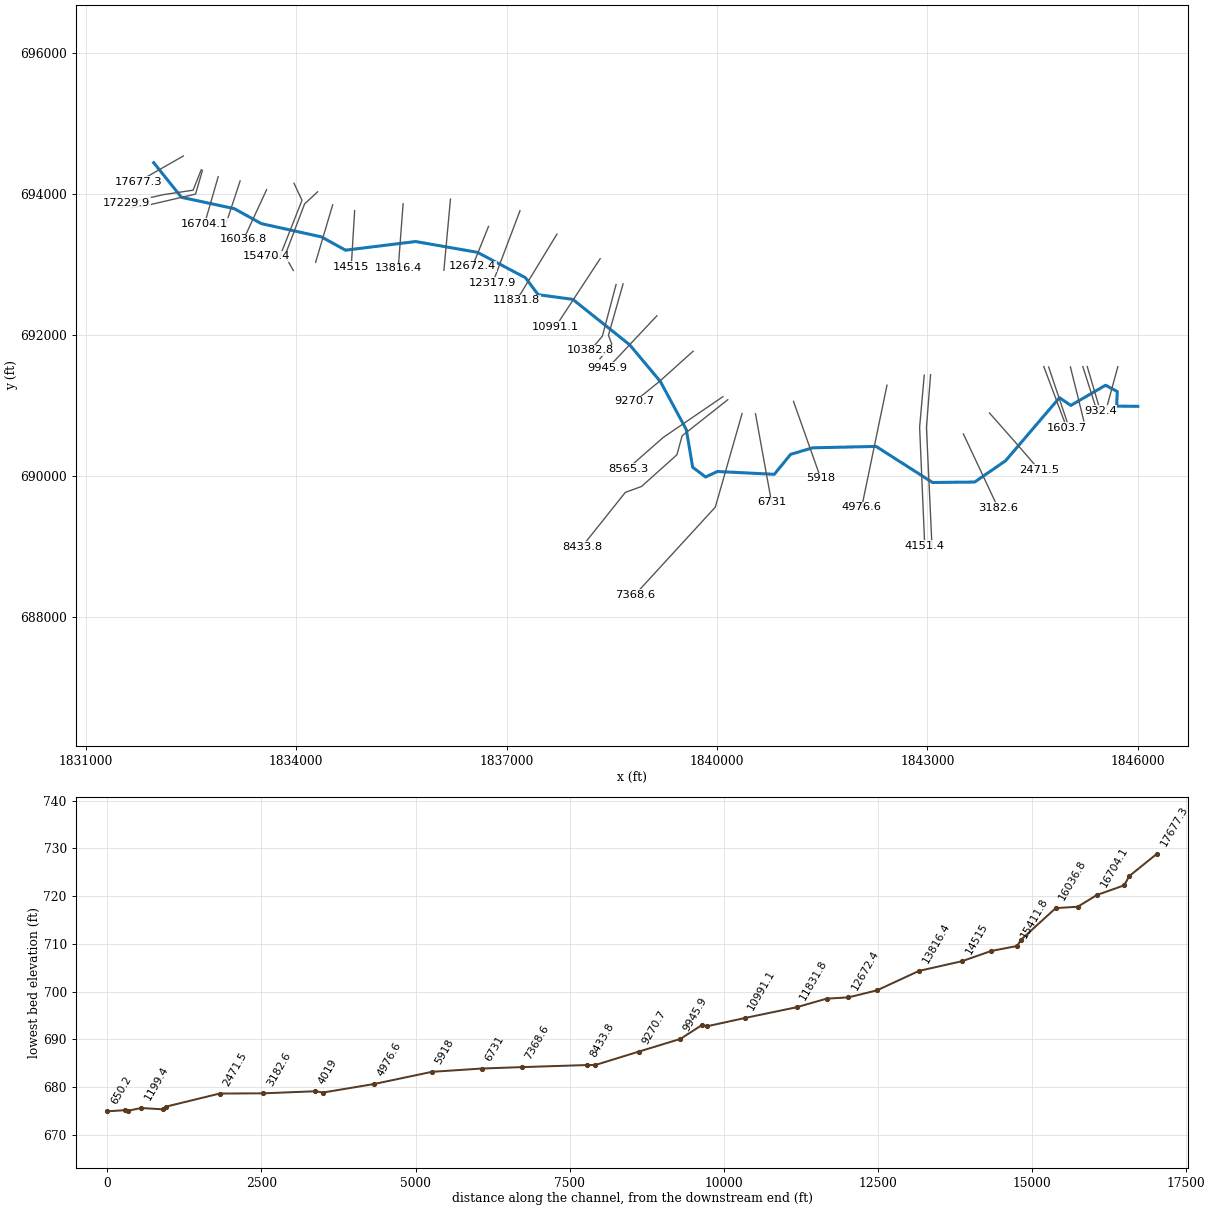
--- RFReedyCrk.prj (project) ---

Proj Title=RFReedyCrk
Current Plan=p01
Default Exp/Contr=0,0
English Units
Geom File=g01
Flow File=f01
Plan File=p01
BEGIN DESCRIPTION:
AMEC Environment & Infrastructure, 2013
Projection: NAD 1983 State Plane West Virginia South FIPS 4702 (US Feet)
Vertical Datum: NAVD 1988
END DESCRIPTION:
DSS Export Rating Curves= 0
DSS Export Rating Curve Sorted= 0
DSS Export Volume Flow Curves= 0
DXF OffsetX= 0
DXF OffsetY= 0
DXF ScaleX= 0
DXF ScaleY= 0

--- RFReedyCrk.p01 (plan) ---

Plan Title=Floodplain
Program Version=4.00
Geom File=g01
Flow File=f01
K Sum by GR=0
Std Step Tol=0.01
Critical Tol=0.01
Num of Std Step Trials=20
Max Error Tol=0.3
Flow Tol Ratio=0.001
Split Flow NTrial=30
Split Flow Tol=0.02
Split Flow Ratio=0.02
Log Output Level=0
Friction Slope Method=1
Unsteady Friction Slope Method=2
Unsteady Bridges Friction Slope Method=1
Global Log Level=0
CheckData=False
Run HTab=0
Run UNet=0
Run PostProcess=0
UNET Theta=0
UNET Theta Warmup=0
UNET ZTol=0
UNET ZSATol=0
UNET MxIter=0
UNET MaxInSteps=0
UNET DtIC=0
UNET DtMin=0
UNET MaxCRTS=0
UNET WFStab=0
UNET SFStab=0
UNET WFX=0
UNET SFX=0
UNET DSS MLevel=0
UNET DZMax Abort=0
UNET Convert EG Bridges=0
UNET Use Existing IB Tables=0
UNET Froude Limit=0
UNET Froude Power=0
Write IC File=0
Echo Input=False
Echo Output=False
Write Detailed=0

--- RFReedyCrk.f01 (steady flow) ---

Flow Title=NFF Regression Equation
Program Version=4.00
Number of Profiles=1
Profile Names=P100yr
River Rch & RM=RFReedyCrk,Main      ,17677.3
1002.064
River Rch & RM=RFReedyCrk,Main      ,15470.4
1109.536
River Rch & RM=RFReedyCrk,Main      ,14988.8
1225.039
River Rch & RM=RFReedyCrk,Main      ,11831.8
1308.305
River Rch & RM=RFReedyCrk,Main      ,10991.1
1656.889
River Rch & RM=RFReedyCrk,Main      ,8565.3
1763.811
River Rch & RM=RFReedyCrk,Main      ,7368.6
2668.241
River Rch & RM=RFReedyCrk,Main      ,1199.4
2858.562
River Rch & RM=RFReedyCrk,Main      ,932.4
2860.264
Boundary for River Rch & Prof#=RFReedyCrk,Main      ,1
Up Type=0
Dn Type=3
Dn Slope=0.001808

--- RFReedyCrk.g01 (geometry) ---

Geom Title=USGS 3m DEM
Program Version=4.10

River Reach=RFReedyCrk      ,Main
Reach XY= 30
     1831967.176      694445.836     1832363.377      693954.193
     1833116.497      693793.148     1833502.427      693580.251
     1834358.326      693392.054     1834702.598      693203.227
     1835701.908      693326.041     1836583.604      693172.508
     1837267.475      692812.202     1837449.856      692570.804
     1837943.106      692504.845     1838754.232      691858.827
      1839191.94      691337.827     1839561.927      690653.566
      1839652.28      690120.382     1839836.389      689981.454
      1840004.85      690059.622     1840815.929      690019.737
     1841048.635       690302.85     1841362.368      690396.044
     1842267.845      690415.832     1843072.012      689903.543
     1843673.282      689910.174      1844112.32       690211.03
     1844882.476      691108.132     1845043.176       690997.86
     1845539.667      691284.819     1845706.229      691196.266
     1845697.796      690987.536     1845999.295      690985.427

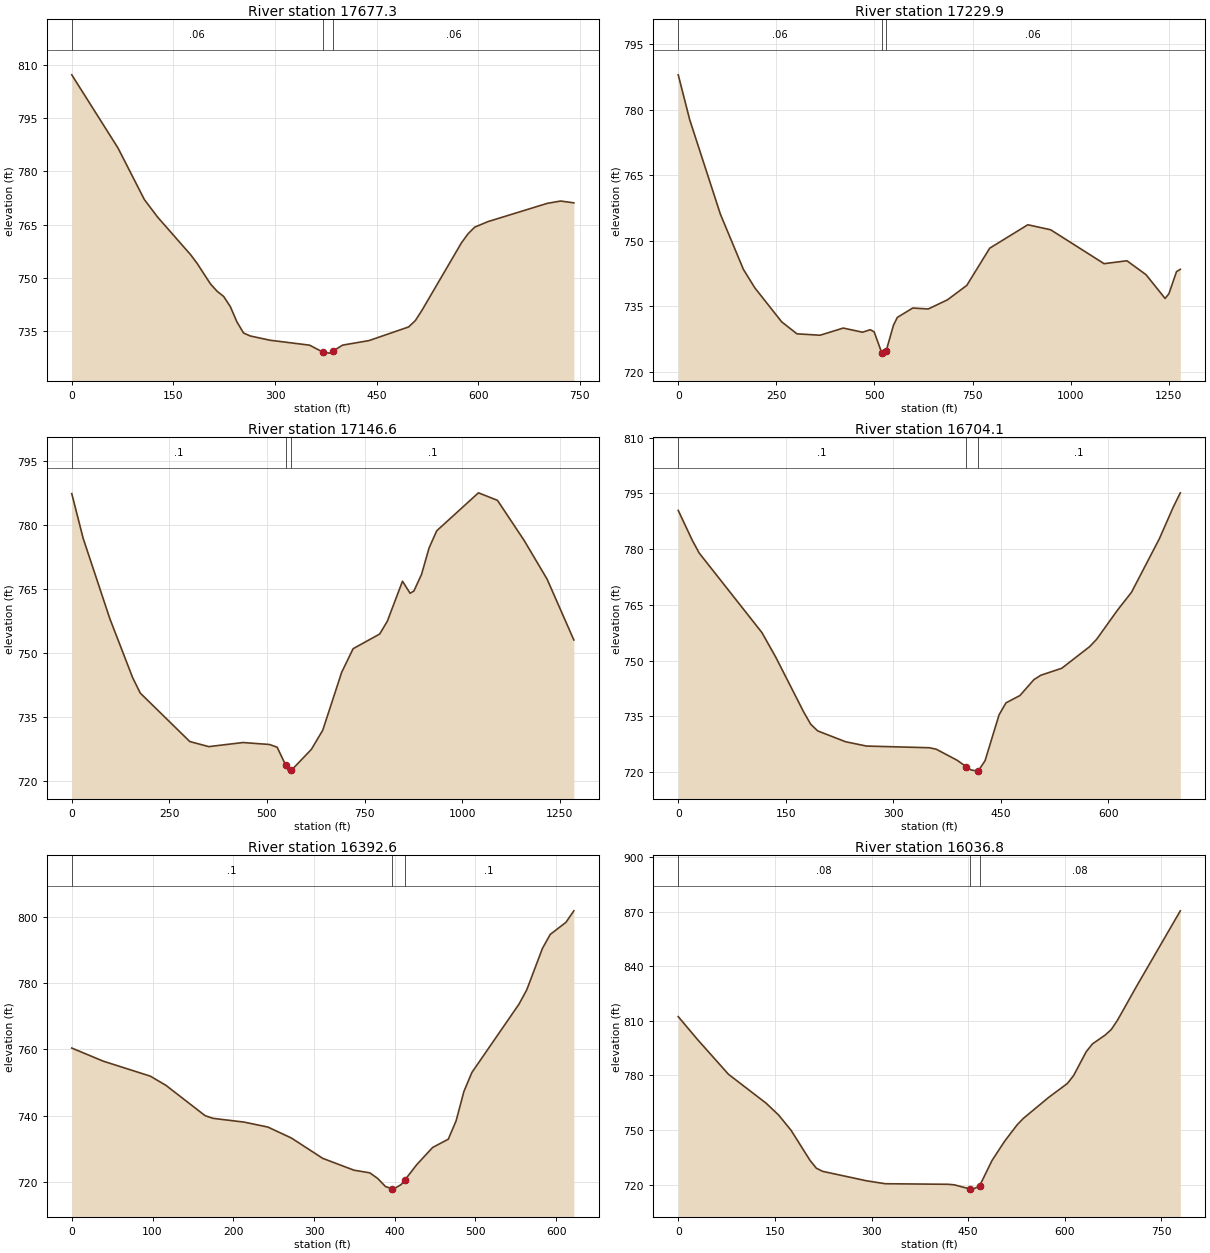
Type RM Length L Ch R = 1 ,17677.3 ,454.3,447.4,433.1
XS GIS Cut Line= 2
     1832390.143      694541.304     1831746.045      694174.985
#Sta/Elev= 30
       0  807.16    68.2  786.58   107.2  772.05   126.8  767.11   175.5  756.53
   185.2  754.06   204.7  748.33   214.5  746.27   224.2   744.8     234  741.95
   243.7  737.67   253.5  734.53   263.2   733.7   292.5  732.49     351   731.1
   370.5  729.16   380.2  728.86   385.5  729.43   399.7  731.11   438.7  732.39
   497.2  736.23     507     738   516.7  740.86   575.2  759.92     585  762.46
   594.7   764.3   614.2  765.86     702  771.01   721.5  771.65     741  771.14
#Mann= 3 , 0 , 0
       0     .06       0   370.5    .045       0   385.5     .06       0
Bank Sta=370.5,385.5
XS Rating Curve= 0 ,0
Exp/Cntr=0.3,0.1

Type RM Length L Ch R = 1 ,17229.9 ,92.6,83.4,84.5
XS GIS Cut Line= 4
     1832645.351      694345.124     1832529.032      694055.193
     1832110.629      693992.693     1831579.379      693874.637
#Sta/Elev= 30
       0  787.95    29.3  777.66   107.4  756.04     166  743.41   195.2  739.16
   263.6  731.38   302.6  728.63   361.6  728.31   420.6  729.95   469.8     729
   489.5  729.57   499.3  729.09     519  724.21   530.2  724.79   548.5  730.59
   558.4  732.39   597.7  734.54   637.1  734.32   686.2  736.42   735.4  739.72
   793.8  748.24   890.9  753.61   949.2  752.46  1085.3   744.7  1143.6  745.36
  1192.2  742.18  1240.8  736.73  1250.5   737.8  1269.9  742.87  1279.6   743.4
#Mann= 3 , 0 , 0
       0     .06       0     519    .045       0   530.2     .06       0
Bank Sta=519,530.2
XS Rating Curve= 0 ,0
Exp/Cntr=0.3,0.1

Type RM Length L Ch R = 1 ,17146.6 ,405.1,442.5,465.6
XS GIS Cut Line= 4
     1832662.712      694336.443     1832563.754      693999.637
     1831843.268      693832.971     1831648.823      693810.401
#Sta/Elev= 30
       0  787.38    29.2  776.89    97.5  758.05     156  744.19   175.5  740.58
   302.3  729.21     351  728.01   438.6  728.97   506.7  728.51   526.2  727.87
   547.9  723.71   555.4  722.26   562.9  722.49   613.8  727.36     643  731.86
   691.6  745.48   720.8  750.99   788.9  754.44   808.4  757.43   847.3  766.83
   866.8     764   876.5  764.53     896   768.4   915.4  774.63   934.9  778.65
  1041.9  787.57  1090.6  785.81  1159.1  776.38  1217.8  767.31  1286.3  753.04
#Mann= 3 , 0 , 0
       0      .1       0   547.9    .045       0   562.9      .1       0
Bank Sta=547.9,562.9
XS Rating Curve= 0 ,0
Exp/Cntr=0.3,0.1

Type RM Length L Ch R = 1 ,16704.1 ,312.2,311.5,310.4
XS GIS Cut Line= 2
     1832887.365      694247.554     1832692.052      693574.811
#Sta/Elev= 30
       0  790.44    19.5  782.43    29.2  778.97   116.8  757.53   136.2  750.87
   175.1  736.13   184.9  732.84   194.6  731.06   233.5  728.14   262.7  726.98
   350.3  726.53     360  726.13   389.2  723.15   401.6  721.45   408.6  720.54
   418.4  720.23   428.1  723.04   447.6  735.38   457.3  738.62   476.7  740.58
   496.2  744.86   505.9  746.05   535.1  747.93     574  753.75   583.8  755.74
     613  763.62   632.4  768.39   671.3  782.82   690.8  791.39   700.5  795.17
#Mann= 3 , 0 , 0
       0      .1       0   401.6    .045       0   418.4      .1       0
Bank Sta=401.6,418.4
XS Rating Curve= 0 ,0
Exp/Cntr=0.3,0.1

Type RM Length L Ch R = 1 ,16392.6 ,358,355.8,352.9
XS GIS Cut Line= 2
     1833199.865       694186.79     1833004.552      693596.512
#Sta/Elev= 30
       0  760.42    38.9  756.46    97.2  751.93   116.6  749.15   165.2  739.97
   174.9  739.17   213.7  738.02   242.9  736.53     272  733.22   310.9  727.06
   349.7  723.48   369.2  722.69   378.9  720.99   388.6  718.54   397.2  717.86
   398.3  717.77     408  719.17   412.2  720.43   427.4  725.21   446.9  730.36
   466.3  732.86     476  738.43   485.7  747.33   495.5  753.02   553.8  773.67
   563.5  778.02   582.9  790.54   592.6  794.78     612  798.42   621.8   801.9
#Mann= 3 , 0 , 0
       0      .1       0   397.2    .045       0   412.2      .1       0
Bank Sta=397.2,412.2
XS Rating Curve= 0 ,0
Exp/Cntr=0.3,0.1

Type RM Length L Ch R = 1 ,16036.8 ,564.6,566.4,567.4
XS GIS Cut Line= 2
      1833577.11       694062.24     1833249.347      693355.295
#Sta/Elev= 30
       0  812.36    29.2  800.07    77.9  780.67   136.4  764.75   155.8  758.24
   175.3  749.75   204.6  733.27   214.3  729.01     224  727.28   292.2  722.07
   321.4  720.46   418.8  720.15   428.6  719.84   452.8  717.58   457.8  717.49
   467.8  719.33     487  733.25   506.5  743.81     526  752.86   535.7  756.42
   574.7  767.88   603.9  775.58   613.6  779.94   633.1  793.02   642.9  797.37
   662.4  802.16   672.1  805.28   681.8  810.44     711  828.85   779.2  870.54
#Mann= 3 , 0 , 0
       0     .08       0   452.8    .045       0   467.8     .08       0
Bank Sta=452.8,467.8
XS Rating Curve= 0 ,0
Exp/Cntr=0.3,0.1

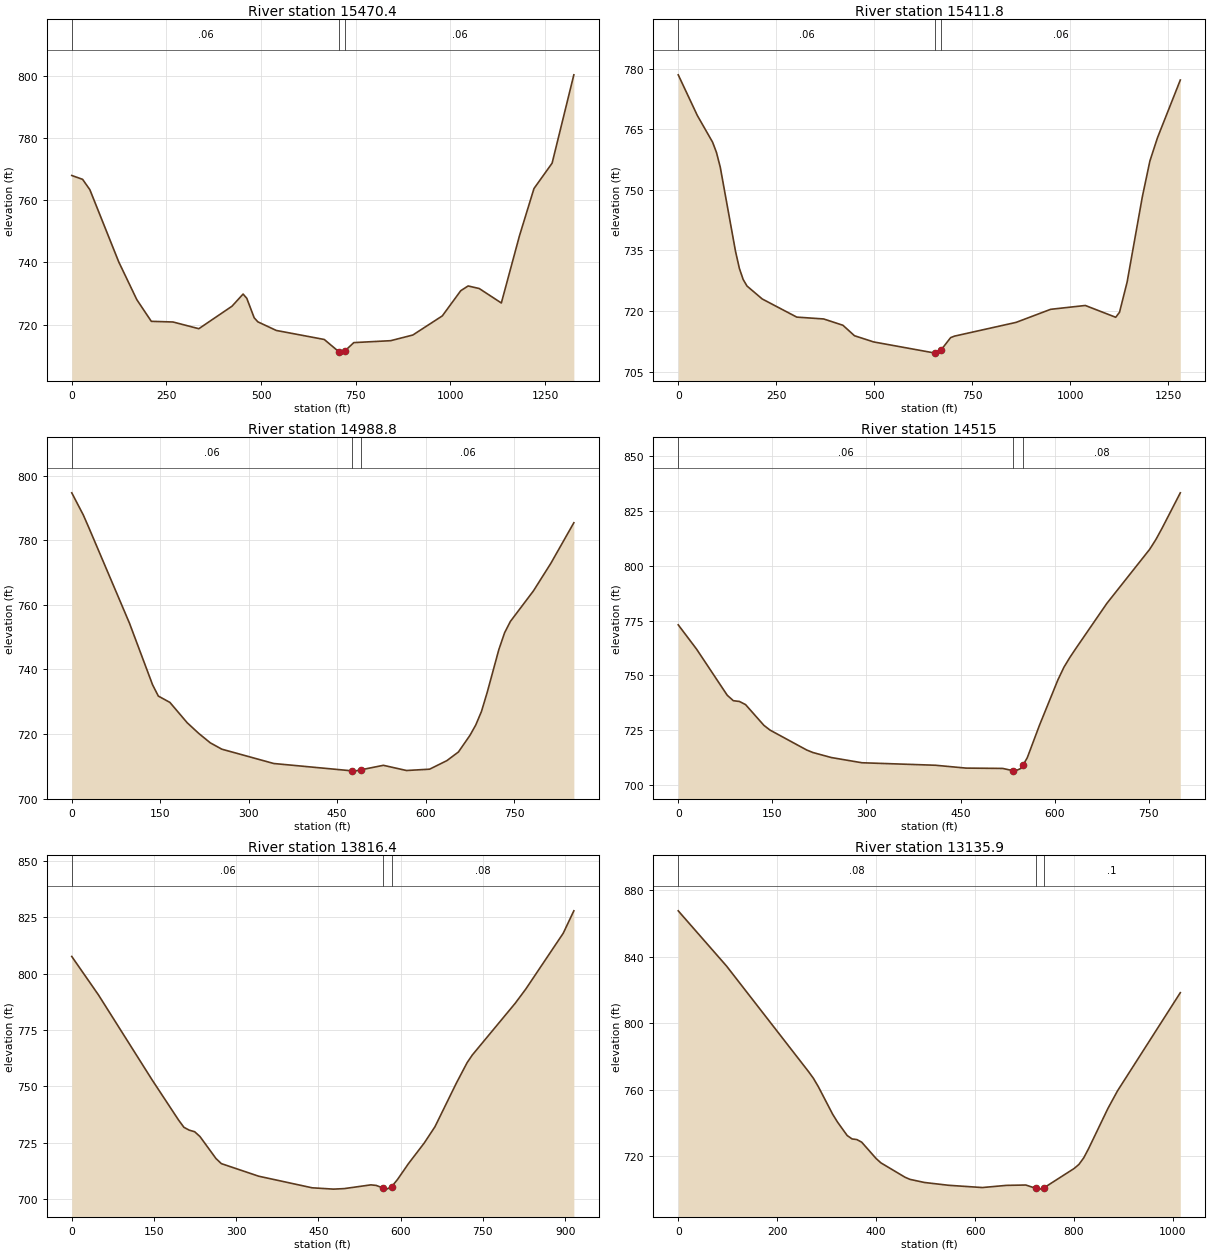
Type RM Length L Ch R = 1 ,15470.4 ,58.3,58.6,58.9
XS GIS Cut Line= 4
     1833968.097      694153.906     1834081.819       693911.92
     1833763.236      693105.295     1833572.263      693119.184
#Sta/Elev= 30
       0  767.94    28.6   766.7    47.8  763.37   124.1  740.15   171.9     728
   210.1  721.05   267.4  720.84   335.6  718.68   423.3  725.92   452.5  729.82
   462.3  728.45   481.8  722.19   491.5  720.89   540.2  718.12   666.9  715.22
   706.4  711.18   715.6  710.83   721.4  711.54   744.9  714.21   842.3  714.83
   900.8  716.65   978.7   722.8  1027.4   730.9  1046.9  732.42  1076.2   731.6
  1134.6  726.95  1182.5  748.56  1220.8  763.74  1268.7   771.9  1326.1   800.3
#Mann= 3 , 0 , 0
       0     .06       0   706.4    .045       0   721.4     .06       0
Bank Sta=706.4,721.4
XS Rating Curve= 0 ,0
Exp/Cntr=0.3,0.1

Type RM Length L Ch R = 1 ,15411.8 ,421.3,423,424.6
XS GIS Cut Line= 4
     1834304.902      694032.378     1834118.721      693860.418
     1833839.624      693126.128      1833957.68      692914.323
#Sta/Elev= 30
       0  778.47    48.7  768.41    87.7  761.79    97.5  759.27   107.2  755.64
   146.2  734.77     156  730.56   165.7  727.79   175.5  726.17   214.4  722.96
   302.5  718.47   371.3  718.01   420.4  716.45   449.8  713.86   498.9  712.32
     655  709.57     656  709.55     670  710.23   695.3  713.39   705.1  713.76
   862.2  717.16   950.6   720.4    1039  721.35  1116.6  718.43  1126.3  719.66
  1145.7  727.13  1184.5  748.23  1203.9  757.14  1223.3  762.91  1281.5  777.18
#Mann= 3 , 0 , 0
       0     .06       0     655    .045       0     670     .06       0
Bank Sta=655,670
XS Rating Curve= 0 ,0
Exp/Cntr=0.3,0.1

Type RM Length L Ch R = 1 ,14988.8 ,468.5,473.8,478.8
XS GIS Cut Line= 2
     1834519.312      693847.482     1834276.256       693031.51
#Sta/Elev= 30
       0  794.68    19.6  787.81    29.4  783.71    97.9  754.29     137  735.25
   146.8  731.74   166.4  729.78   195.7  723.49   215.3  720.18   234.9  717.26
   254.4   715.3   342.5  710.86   475.7  708.58   479.5   708.5   490.7  708.92
   528.5   710.3   567.6  708.69   606.8   709.1   636.1  711.75   655.7  714.43
   675.2  719.57     685  722.76   694.8     727   704.6  732.97   724.2  746.13
     734  751.36   743.8  754.86   782.9  764.32   812.3  772.82   851.4  785.41
#Mann= 3 , 0 , 0
       0     .06       0   475.7    .045       0   490.7     .06       0
Bank Sta=475.7,490.7
XS Rating Curve= 0 ,0
Exp/Cntr=0.3,0.1

Type RM Length L Ch R = 1 ,14515   ,698.9,698.5,698.2
XS GIS Cut Line= 2
      1834832.68      693765.017     1834784.069      692966.406
#Sta/Elev= 30
       0  773.09    29.3  761.98    78.1  740.97    87.8  738.49    97.6  738.13
   107.3   736.7   136.6  727.22   146.4  725.06   204.9  715.97   214.7  714.84
   243.9  712.56   292.7  710.18   409.8  709.04   458.6  707.74   517.1  707.59
   534.1  706.52   536.6  706.36   546.4  707.63   549.1  708.96   556.2  712.46
   575.7  727.31     605  747.96   614.7  753.79   624.5  758.41   634.2  762.54
     683  782.86   751.3  807.55   761.1  811.97   770.8  817.04   800.1  833.31
#Mann= 3 , 0 , 0
       0     .06       0   534.1    .045       0   549.1     .08       0
Bank Sta=534.1,549.1
XS Rating Curve= 0 ,0
Exp/Cntr=0.3,0.1

Type RM Length L Ch R = 1 ,13816.4 ,680,680.5,679.7
XS GIS Cut Line= 2
     1835523.652      693862.239     1835454.208      692949.045
#Sta/Elev= 30
       0  807.56    48.7   790.5   146.1  752.97   194.9  734.94   204.6  731.75
   214.3  730.48   224.1   729.8   233.8  727.67   263.1  717.88   272.8  715.64
     341  710.05   438.4  704.91   477.4  704.32   496.9  704.55   545.6  706.21
   555.3  705.96   568.3  704.77   574.8  704.34   583.3  705.35   594.3  708.64
   613.8  715.52     643  724.82   662.5  732.02   701.5  751.36     721  760.39
   730.7  763.87   808.7  786.75   828.2  793.12   896.4  817.86   915.8  827.82
#Mann= 3 , 0 , 0
       0     .06       0   568.3    .045       0   583.3     .08       0
Bank Sta=568.3,583.3
XS Rating Curve= 0 ,0
Exp/Cntr=0.3,0.1

Type RM Length L Ch R = 1 ,13135.9 ,469.8,463.4,456.5
XS GIS Cut Line= 2
     1836198.999      693928.211     1836105.249      692917.795
#Sta/Elev= 30
       0  867.67    97.6  834.47   263.4  770.94   273.2  766.92     283  761.98
   312.2  745.26     322  740.57   341.5  732.49   351.3  730.45     361  730.06
   370.8   728.5     400  718.64   409.8  716.02   458.6  707.37   468.4  706.12
   497.6  704.25   546.4  702.56   614.7   701.2   663.5  702.51   702.5  702.72
   723.4  700.67   731.8  700.25   738.4  700.88   800.1  712.65   809.8  715.09
   819.6  719.08   829.4   724.6   868.4  748.73   887.9  759.38  1014.8  818.42
#Mann= 3 , 0 , 0
       0     .08       0   723.4    .045       0   738.4      .1       0
Bank Sta=723.4,738.4
XS Rating Curve= 0 ,0
Exp/Cntr=0.3,0.1

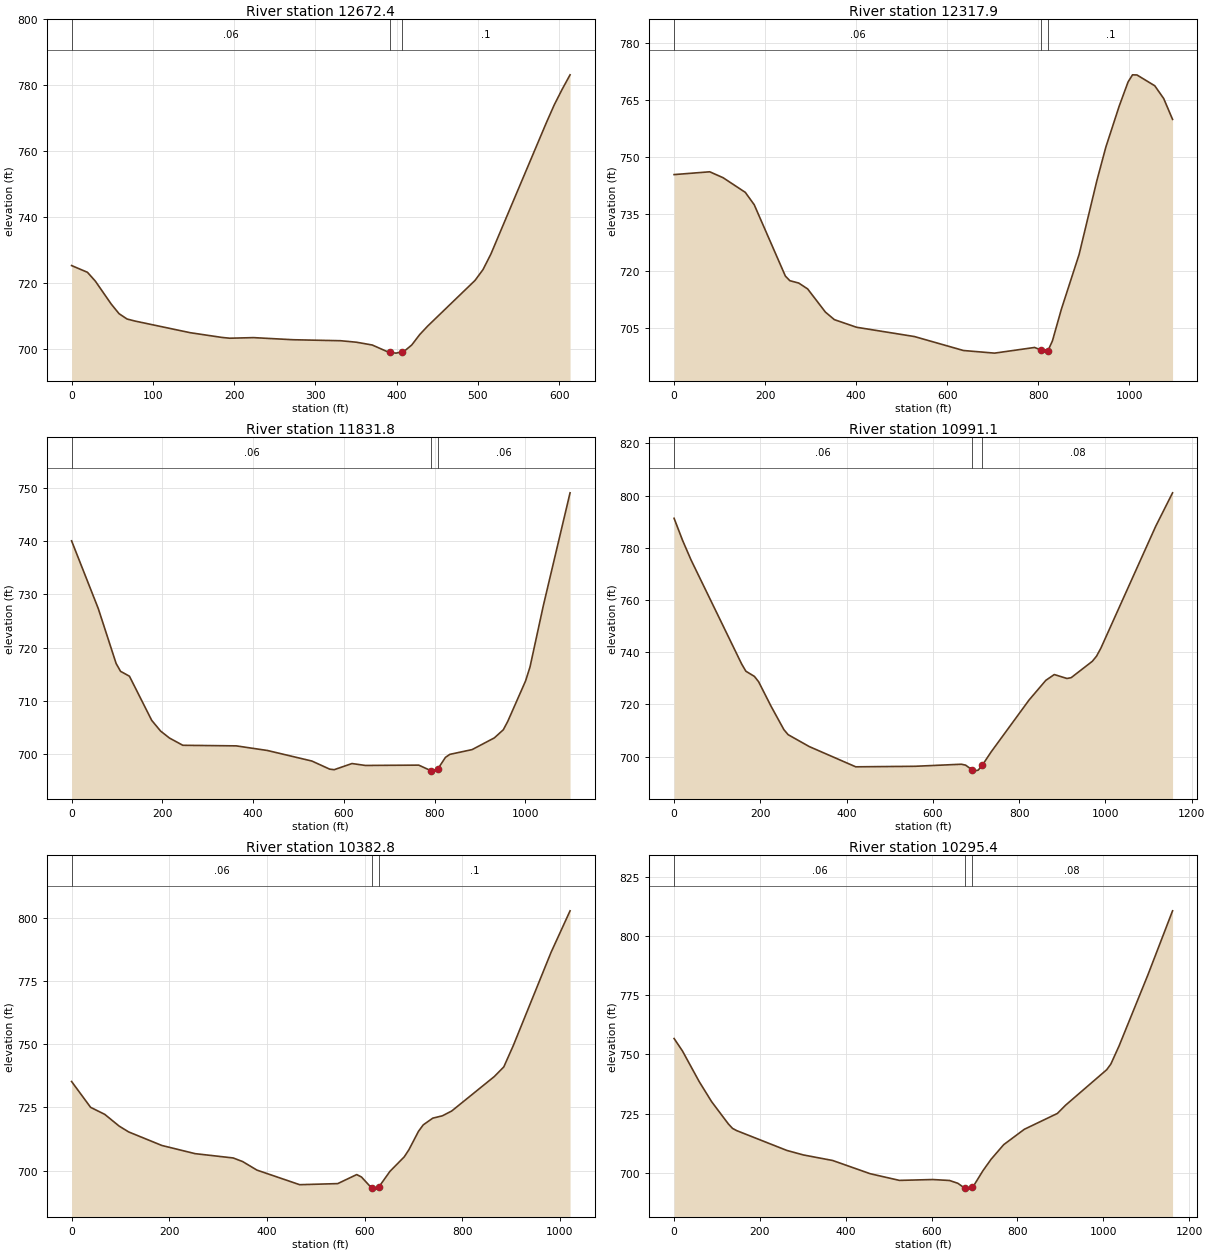
Type RM Length L Ch R = 1 ,12672.4 ,354,354.5,354.8
XS GIS Cut Line= 2
     1836741.532      693540.089     1836511.497      692971.512
#Sta/Elev= 30
       0  725.33    19.5  723.29    29.2  720.62    48.7  713.68    58.4  710.74
    68.2  709.13    77.9  708.51     146  704.97     185  703.54   194.7   703.3
   223.9  703.48   272.6  702.84     331  702.54   350.5  702.09     370  701.24
   389.4  699.13     392  699.04   399.2  698.78     407  699.17   408.9  699.27
   418.6  701.25   428.4  704.41   438.1  706.96   496.5  720.84   506.3  724.12
     516  728.83   584.1  768.57   593.9  774.03   603.6  778.74   613.4  783.16
#Mann= 3 , 0 , 0
       0     .06       0     392    .045       0     407      .1       0
Bank Sta=392,407
XS Rating Curve= 0 ,0
Exp/Cntr=0.3,0.1

Type RM Length L Ch R = 1 ,12317.9 ,487.5,486.1,482.3
XS GIS Cut Line= 2
     1837190.319      693764.149      1836801.43      692739.843
#Sta/Elev= 30
       0  745.46    78.3   746.2   107.6  744.65   156.5  740.79   176.1  737.54
   244.6  718.77   254.4  717.56   273.9  716.94   293.5   715.4   332.6   709.3
   352.2  707.32   401.1  705.31   528.3  702.87   635.9   699.2   704.3  698.51
   792.4     700   806.3  699.32   821.7  699.15   831.5  701.71   851.1  710.02
   890.2  724.47   929.3  743.91   948.9  752.67   978.2  763.44   997.8  769.83
  1007.6   771.7  1017.4  771.66  1056.5  768.82  1076.1  765.47  1095.6  759.98
#Mann= 3 , 0 , 0
       0     .06       0   806.3    .045       0   821.7      .1       0
Bank Sta=806.3,821.7
XS Rating Curve= 0 ,0
Exp/Cntr=0.3,0.1

Type RM Length L Ch R = 1 ,11831.8 ,835.4,840.7,838.6
XS GIS Cut Line= 2
     1837717.229      693431.684     1837144.312      692494.184
#Sta/Elev= 30
       0  740.11    58.9  727.33    98.1  717.01   107.9  715.52   127.5   714.6
   176.6  706.28   196.2  704.26   215.8  702.94   245.2  701.58     363  701.47
   431.6   700.6   529.7  698.61     569  697.08   578.8  696.98     618  698.14
   647.4  697.78   765.2  697.84   792.8  696.76   794.6  696.71   807.8  697.19
     824   699.3   833.8  699.87   882.9  700.77   931.9  702.98   951.6  704.51
   961.4  706.09  1000.6   713.7  1010.4  716.34  1039.8  727.91  1098.7  749.16
#Mann= 3 , 0 , 0
       0     .06       0   792.8    .045       0   807.8     .06       0
Bank Sta=792.8,807.8
XS Rating Curve= 0 ,0
Exp/Cntr=0.3,0.1

Type RM Length L Ch R = 1 ,10991.1 ,600.2,608.3,614.9
XS GIS Cut Line= 2
     1838333.548      693082.725     1837698.131      692117.448
#Sta/Elev= 30
       0  791.27    19.6  782.85    39.2  775.36   156.7  735.45   166.5   732.7
   186.1  730.74   195.9   728.7   225.2  719.17   254.6  710.33   264.4  708.41
   313.4  703.85   421.1   696.1   558.2   696.3     666  697.09   675.8  696.74
   691.6  694.86   695.4  694.45   705.1  694.84   714.9   696.8   734.5   701.7
   822.7  721.64   861.8  729.22   881.4  731.44   910.8  729.93   920.6  730.25
   969.6  736.51   979.4   738.5   989.2  741.47  1116.5  788.21  1155.6  801.03
#Mann= 3 , 0 , 0
       0     .06       0   691.6    .045       0   714.9     .08       0
Bank Sta=691.6,714.9
XS Rating Curve= 0 ,0
Exp/Cntr=0.3,0.1

Type RM Length L Ch R = 1 ,10382.8 ,86.9,87.4,86.8
XS GIS Cut Line= 3
     1838560.108      692715.436     1838364.795      691981.929
     1838195.525      691782.276
#Sta/Elev= 30
       0  735.24    38.9  725.04    68.1  722.24    97.3  717.64   116.8  715.33
   184.9  709.97     253  706.74   330.9  705.04   350.3  703.62   379.5  700.25
   467.1  694.48     545  694.91   583.9  698.48   593.6  697.52   614.4  693.18
   622.8  692.73   629.4  693.63     652  699.76   681.2  705.47   690.9  708.33
   710.4  715.56   720.1   718.1   739.6  720.76   759.1  721.67   778.4  723.58
   865.7   737.2   885.1     741   904.5  749.41     982  786.31  1020.8  802.65
#Mann= 3 , 0 , 0
       0     .06       0   614.4    .045       0   629.4      .1       0
Bank Sta=614.4,629.4
XS Rating Curve= 0 ,0
Exp/Cntr=0.3,0.1

Type RM Length L Ch R = 1 ,10295.4 ,361.1,349.5,338.7
XS GIS Cut Line= 4
     1838659.934      692724.117     1838451.601       691994.95
     1838499.344      691869.082     1838330.073      691660.749
#Sta/Elev= 30
       0  756.76    19.4  751.52    58.3  738.58    87.5     730   126.4   720.6
   136.1  718.71   145.8  717.76   262.5  709.38   301.4  707.45   369.4  705.11
     457   699.5     525  696.68   602.8  697.04   641.7  696.64   661.1  695.46
   678.1  693.26   680.6  692.98   693.1   693.7     700     695   719.5  700.76
   738.9   705.7     768  711.82     816  718.32     893  725.03   912.1  728.52
    1008  743.56  1017.6  745.94  1036.8  753.64  1103.9   783.7  1161.4  810.84
#Mann= 3 , 0 , 0
       0     .06       0   678.1    .045       0   693.1     .08       0
Bank Sta=678.1,693.1
XS Rating Curve= 0 ,0
Exp/Cntr=0.3,0.1

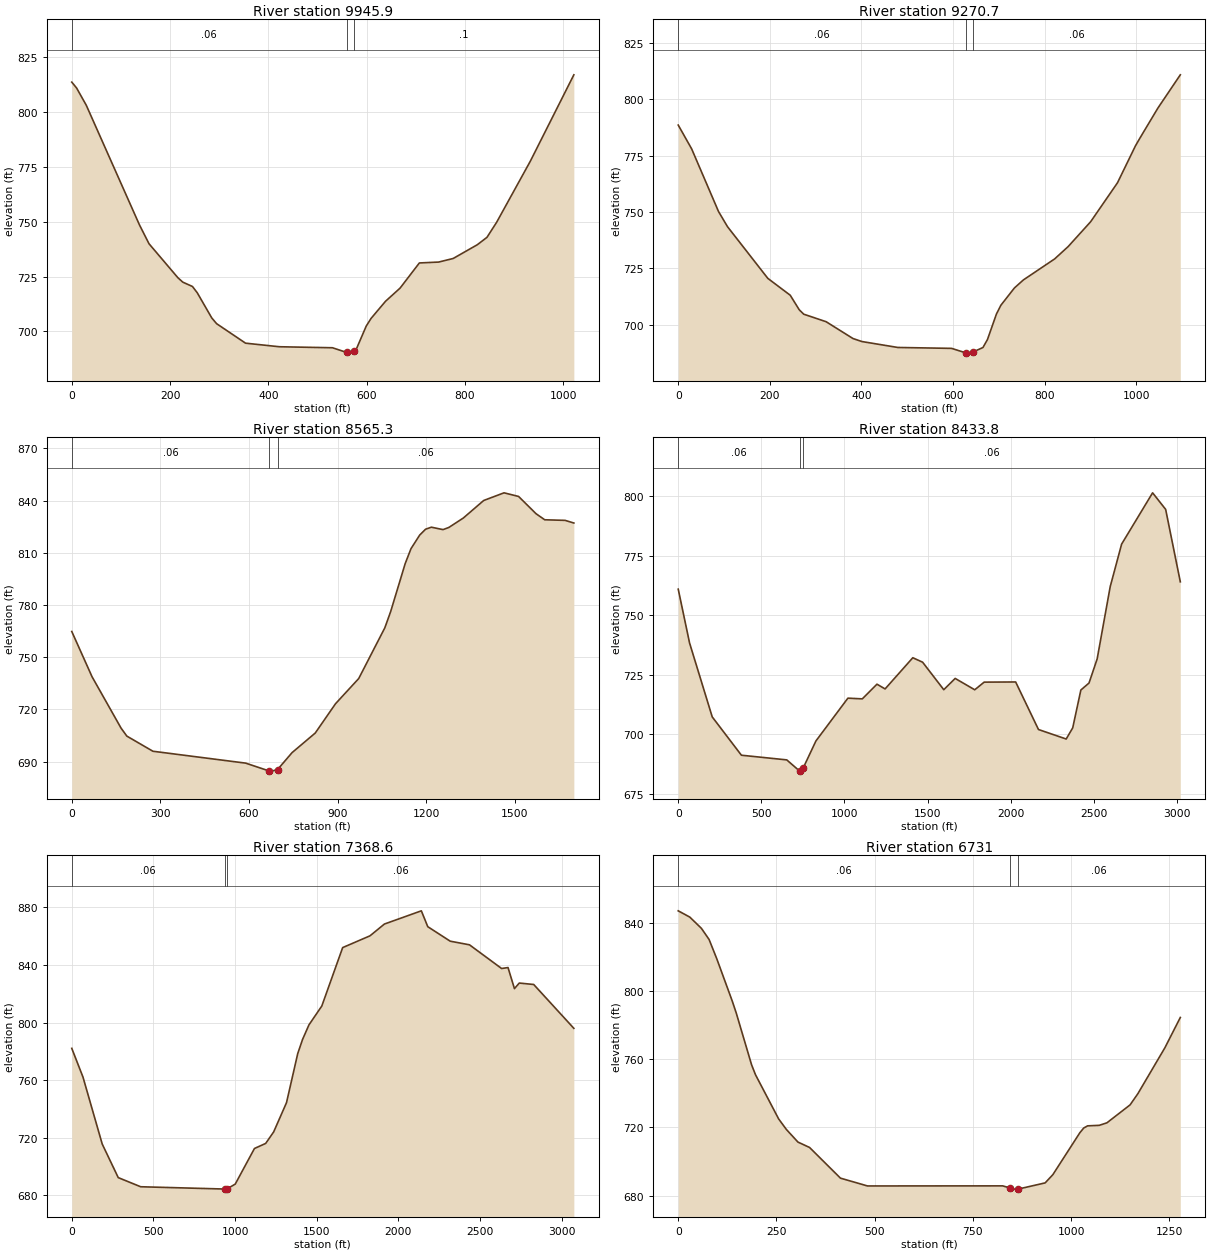
Type RM Length L Ch R = 1 ,9945.9  ,677,675.2,672
XS GIS Cut Line= 2
     1839142.576      692271.961     1838441.187      691528.906
#Sta/Elev= 30
       0  813.72     9.8  811.05    29.5  803.18   137.6  748.66   157.2  739.98
   216.2  724.42     226  722.45   245.6  720.48   255.4   717.6   284.9  706.13
   294.8   703.5   353.7  694.61   422.5  692.98   530.6  692.52   559.7  690.36
   569.8  690.07   574.7  691.12   579.7  692.19   599.3  702.42   609.2  705.93
   638.6  713.74   668.1  719.72   707.4  731.21   746.7  731.62   776.2  733.25
   825.3  739.52     845   742.9   864.6  749.74   933.4  777.71  1021.8  817.05
#Mann= 3 , 0 , 0
       0     .06       0   559.7    .045       0   574.7      .1       0
Bank Sta=559.7,574.7
XS Rating Curve= 0 ,0
Exp/Cntr=0.3,0.1

Type RM Length L Ch R = 1 ,9270.7  ,708.1,705.4,703.2
XS GIS Cut Line= 3
     1839659.069      691768.489     1839185.434      691344.332
     1838826.967      691055.732
#Sta/Elev= 30
       0  788.57    29.3  778.02      88  750.21   107.6  743.49   195.6  720.57
   244.5  713.09   264.1  706.65   273.9  704.69   322.8  701.35   381.5  693.88
     401  692.55   479.3  689.92   596.7  689.52   628.3  687.49   635.8  687.41
   643.3  687.88   665.2  689.91     675  693.42   694.6  704.75   704.3  708.64
   733.7  716.28   753.3  719.86   821.8  729.22   851.2  734.68   900.2  745.68
   958.9  762.99   998.1  779.37  1007.9  782.82    1047   796.1    1096  810.87
#Mann= 3 , 0 , 0
       0     .06       0   628.3    .045       0   643.3     .06       0
Bank Sta=628.3,643.3
XS Rating Curve= 0 ,0
Exp/Cntr=0.3,0.1

Type RM Length L Ch R = 1 ,8565.3  ,127.6,131.4,132.7
XS GIS Cut Line= 3
     1840083.545      691122.554     1839231.986      690542.795
     1838728.513      690101.823
#Sta/Elev= 30
       0  764.81    68.7  738.79   166.8  709.32   186.4  704.72   274.7  696.02
   588.7  689.19   667.2  684.74     677   684.6   696.6   685.5   745.7  695.22
   824.2  706.48   892.8  723.31   971.3  737.77  1059.7  766.91  1079.4  776.22
  1128.6  803.79  1148.3  812.38  1177.8  820.19  1197.5  823.53  1217.2   824.7
  1256.6  823.31  1276.2  824.53  1325.4  829.97  1394.4  840.04  1463.2  844.44
  1512.5  842.35  1571.5  832.44    1601  828.96  1669.9  828.62  1699.5   827.1
#Mann= 3 , 0 , 0
       0     .06       0   667.2    .045       0   696.6     .06       0
Bank Sta=667.2,696.6
XS Rating Curve= 0 ,0
Exp/Cntr=0.3,0.1

Type RM Length L Ch R = 1 ,8433.8  ,1048.9,1065.2,1080.1
XS GIS Cut Line= 6
      1840152.99      691079.151     1839501.948      690566.999
     1839428.164      690297.901     1838923.629      689847.184
     1838692.222      689763.141     1838072.839      688990.031
#Sta/Elev= 30
       0  761.03    68.2  738.42   204.6  707.37   380.1  691.28   652.9  689.32
   730.9   684.6   752.1  685.95   828.4  697.27  1020.8  715.25  1107.4  714.95
  1195.6  721.12  1244.6  719.13  1411.3  732.23  1470.2  730.36  1597.6   718.8
  1666.2  723.54  1783.9  718.77  1840.7  721.98  2030.1  722.05  2167.4  702.08
  2334.2  698.09  2373.4  702.78  2422.4  718.67  2471.5  721.61  2520.5  731.75
    2599  762.11  2667.6  779.95    2854   801.5  2932.5  794.55  3020.7  764.13
#Mann= 3 , 0 , 0
       0     .06       0   730.9    .045       0   752.1     .06       0
Bank Sta=730.9,752.1
XS Rating Curve= 0 ,0
Exp/Cntr=0.3,0.1

Type RM Length L Ch R = 1 ,7368.6  ,628.8,637.6,646.3
XS GIS Cut Line= 3
     1840356.986      690883.073     1839975.041      689553.211
     1838829.784      688309.475
#Sta/Elev= 30
       0  782.05    68.7  762.06   186.4  715.53   284.6  692.16     422  685.81
   935.2  684.22     942  684.16   950.2  684.29  1000.9  687.65  1118.7  712.41
  1187.4  715.94  1236.4  723.97  1314.9  744.28  1383.6   778.4  1413.1  788.21
  1452.4  798.37  1531.1  811.49  1658.8   852.1    1826  860.27  1914.4  868.47
  2140.5  877.66  2179.8  866.64  2317.4  856.55  2435.4  854.02    2632  837.56
  2671.3  838.21  2710.6  823.56  2740.1  827.44  2828.6  826.44  3074.3  795.96
#Mann= 3 , 0 , 0
       0     .06       0   935.2    .045       0   950.2     .06       0
Bank Sta=935.2,950.2
XS Rating Curve= 0 ,0
Exp/Cntr=0.3,0.1

Type RM Length L Ch R = 1 ,6731    ,813,813.1,814
XS GIS Cut Line= 2
     1840547.958        690879.6     1840777.124      689622.656
#Sta/Elev= 30
       0     847    29.5  843.31      59  836.73    78.6  830.17    98.3  818.78
   137.6  794.02   147.4  787.27   186.7  756.73   196.6  750.93   255.5  725.04
   275.2  718.85   304.7  711.44   334.2  708.29   412.8  690.31   481.6  685.73
   825.6  685.78   843.1  684.66     855  683.87   864.9  683.89   933.7  687.52
   953.3  692.33  1022.1  716.94    1032   719.7  1041.8  720.96  1071.3  721.26
  1090.9  722.73  1149.9  733.26  1169.6  739.78  1238.4  766.71  1277.7  784.48
#Mann= 3 , 0 , 0
       0     .06       0   843.1    .045       0   864.9     .06       0
Bank Sta=843.1,864.9
XS Rating Curve= 0 ,0
Exp/Cntr=0.3,0.1

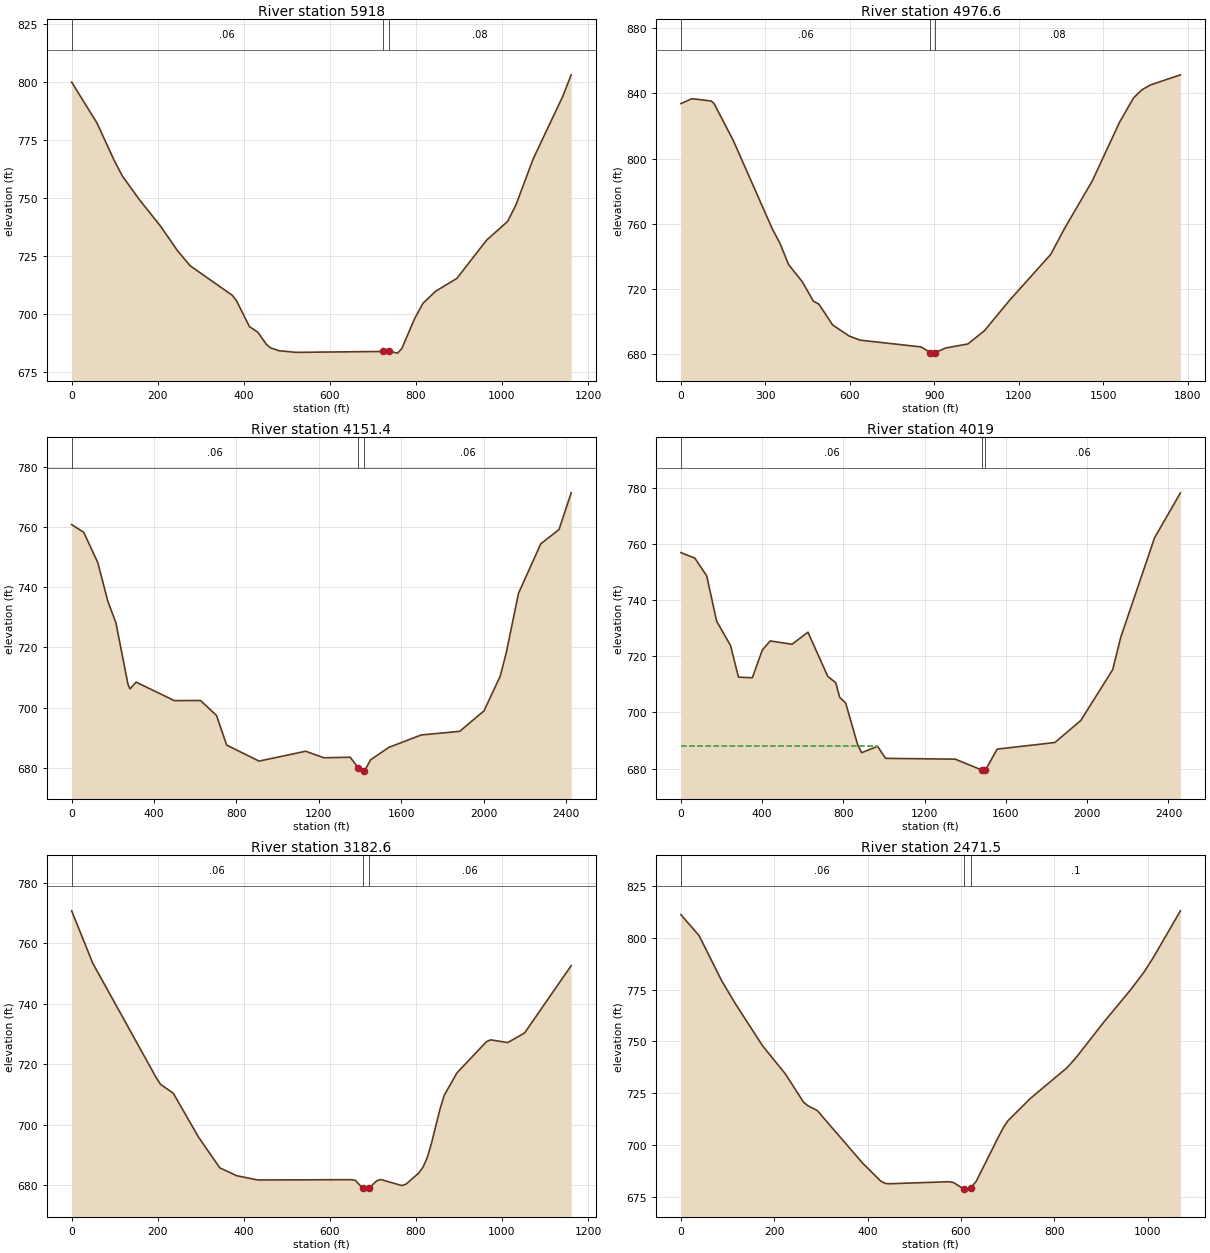
Type RM Length L Ch R = 1 ,5918    ,948.8,941.4,926.6
XS GIS Cut Line= 2
     1841089.624      691056.684     1841478.513      689962.934
#Sta/Elev= 30
       0  799.88      59  782.23    98.4  766.35     118   759.4   157.4  749.28
   206.6  737.85   245.9  727.31   275.4   720.8   373.8  708.02   383.7  705.54
   413.2   694.6   432.8  692.18   452.5  686.96   462.4  685.44     482  684.22
   521.4  683.51   723.3   683.9   738.3  683.98   757.5  683.18   767.3  685.16
   796.8  697.95   816.5  704.65     846  709.85   895.2  715.35   964.1   731.8
  1013.3  739.92  1032.9  747.19  1072.3  766.73  1141.2  793.73  1160.8  803.01
#Mann= 3 , 0 , 0
       0     .06       0   723.3    .045       0   738.3     .08       0
Bank Sta=723.3,738.3
XS Rating Curve= 0 ,0
Exp/Cntr=0.3,0.1

Type RM Length L Ch R = 1 ,4976.6  ,812,825.2,841.2
XS GIS Cut Line= 2
     1842422.958       691285.85     1842061.847      689549.739
#Sta/Elev= 30
       0   833.7    39.2  836.73   107.8  835.32   117.6  833.78   186.1  811.04
   323.3   757.3   352.7   747.6   382.1  735.01   431.1  724.36   470.3  712.54
   489.8  710.69   538.8  697.88   597.6  691.08   636.8  688.56   852.3  684.43
   885.9     681   891.5  680.62   901.3  680.91   940.5  683.78  1018.9  686.25
  1077.7  694.41  1165.8  712.86  1312.8   741.2  1361.8  757.09  1459.8   786.1
  1557.7  822.47  1606.7  837.18  1636.1  842.13  1665.5  845.09  1773.3  851.38
#Mann= 3 , 0 , 0
       0     .06       0   885.9    .045       0   901.3     .08       0
Bank Sta=885.9,901.3
XS Rating Curve= 0 ,0
Exp/Cntr=0.3,0.1

Type RM Length L Ch R = 1 ,4151.4  ,136.7,132.4,126.9
XS GIS Cut Line= 3
     1842954.208      691428.211     1842888.236      690688.628
     1842961.152      689008.073
#Sta/Elev= 30
       0  760.92    58.6  758.35     127  748.25   175.9  735.37   214.9  728.23
   273.6   707.7   283.3   706.2   312.6  708.48   498.3  702.32   625.3  702.35
   703.4  697.36   752.4  687.51   909.8  682.18    1136  685.46  1224.5  683.29
  1352.4  683.47  1391.8  679.82  1411.2  678.84  1421.3  678.84  1450.8  682.59
  1539.3  686.73  1696.7  690.88  1883.6  692.09  2001.7  698.91  2080.4  710.49
  2109.9  718.34  2168.9  738.02  2277.1  754.51  2365.6  759.26  2424.7  771.49
#Mann= 3 , 0 , 0
       0     .06       0  1391.8    .045       0  1421.3     .06       0
Bank Sta=1391.8,1421.3
XS Rating Curve= 0 ,0
Exp/Cntr=0.3,0.1

Type RM Length L Ch R = 1 ,4019    ,828.8,836.4,840.9
XS GIS Cut Line= 3
     1843044.486      691435.156     1842985.458      690685.156
     1843065.319      688980.295
#Sta/Elev= 30
       0   756.9    68.4  754.94     127  748.63   175.9  732.48   244.3  723.82
   283.3  712.55   351.7  712.35   400.6  722.19   439.7  725.45   547.1  724.26
   625.3  728.57     723  712.82   762.1  710.59   781.8  705.38   811.2  703.33
     870  688.54   889.6  685.66   968.1  687.93  1007.4  683.65  1350.7  683.36
  1483.4  679.42    1488   679.1  1498.4  679.35  1556.6  686.93  1841.1  689.29
  1968.6  697.14  2125.6  715.23  2164.8  726.66  2331.5  762.15    2459  778.18
#Mann= 3 , 0 , 0
       0     .06       0  1483.4    .045       0  1498.4     .06       0
#XS Ineff= 2 , 0
          967.98  687.93
Permanent Ineff=
       F       F
Bank Sta=1483.4,1498.4
XS Rating Curve= 0 ,0
Exp/Cntr=0.3,0.1

Type RM Length L Ch R = 1 ,3182.6  ,703.2,711.1,718.1
XS GIS Cut Line= 2
     1843512.365       690593.04     1844007.157      689542.693
#Sta/Elev= 30
       0  770.78    49.2  753.42   196.8   715.5   206.6  713.36   236.2  710.42
   295.2  695.82   344.4  685.72   383.7   683.1   432.9   681.7   649.4   681.8
   659.2   681.6   676.5  678.97   688.8  678.67   691.5  679.01   708.4  681.36
   718.3  681.86   767.5  679.85   777.3  680.33   806.8     684   816.7  685.96
   826.5  689.09   836.4  693.89     856  705.09   865.9  709.71   895.4  717.12
   964.3   727.5   974.1  728.08  1013.5  727.17  1052.8  730.37    1161  752.64
#Mann= 3 , 0 , 0
       0     .06       0   676.5    .045       0   691.5     .06       0
Bank Sta=676.5,691.5
XS Rating Curve= 0 ,0
Exp/Cntr=0.3,0.1

Type RM Length L Ch R = 1 ,2471.5  ,875.5,867.8,858.1
XS GIS Cut Line= 3
     1843884.582       690890.55     1844291.069      690431.856
     1844589.848      690085.936
#Sta/Elev= 30
       0  811.23    38.9  801.13    87.6  779.19   116.7   768.2   175.1  747.82
   223.8  734.28   262.7  720.62   272.4  718.85   291.8  716.67   389.1  691.22
     428  682.51   437.8  681.38   447.5  681.22     574   682.2   583.7  681.83
   605.4  678.74   612.9  678.62   620.4  679.26   632.3  682.29     681  704.23
   690.7  708.33   700.4  711.65     749  722.53   826.8  737.23   846.3  742.13
   904.6  758.96     963  774.86   992.2  783.55  1011.6  790.41    1070  813.09
#Mann= 3 , 0 , 0
       0     .06       0   605.4    .045       0   620.4      .1       0
Bank Sta=605.4,620.4
XS Rating Curve= 0 ,0
Exp/Cntr=0.3,0.1

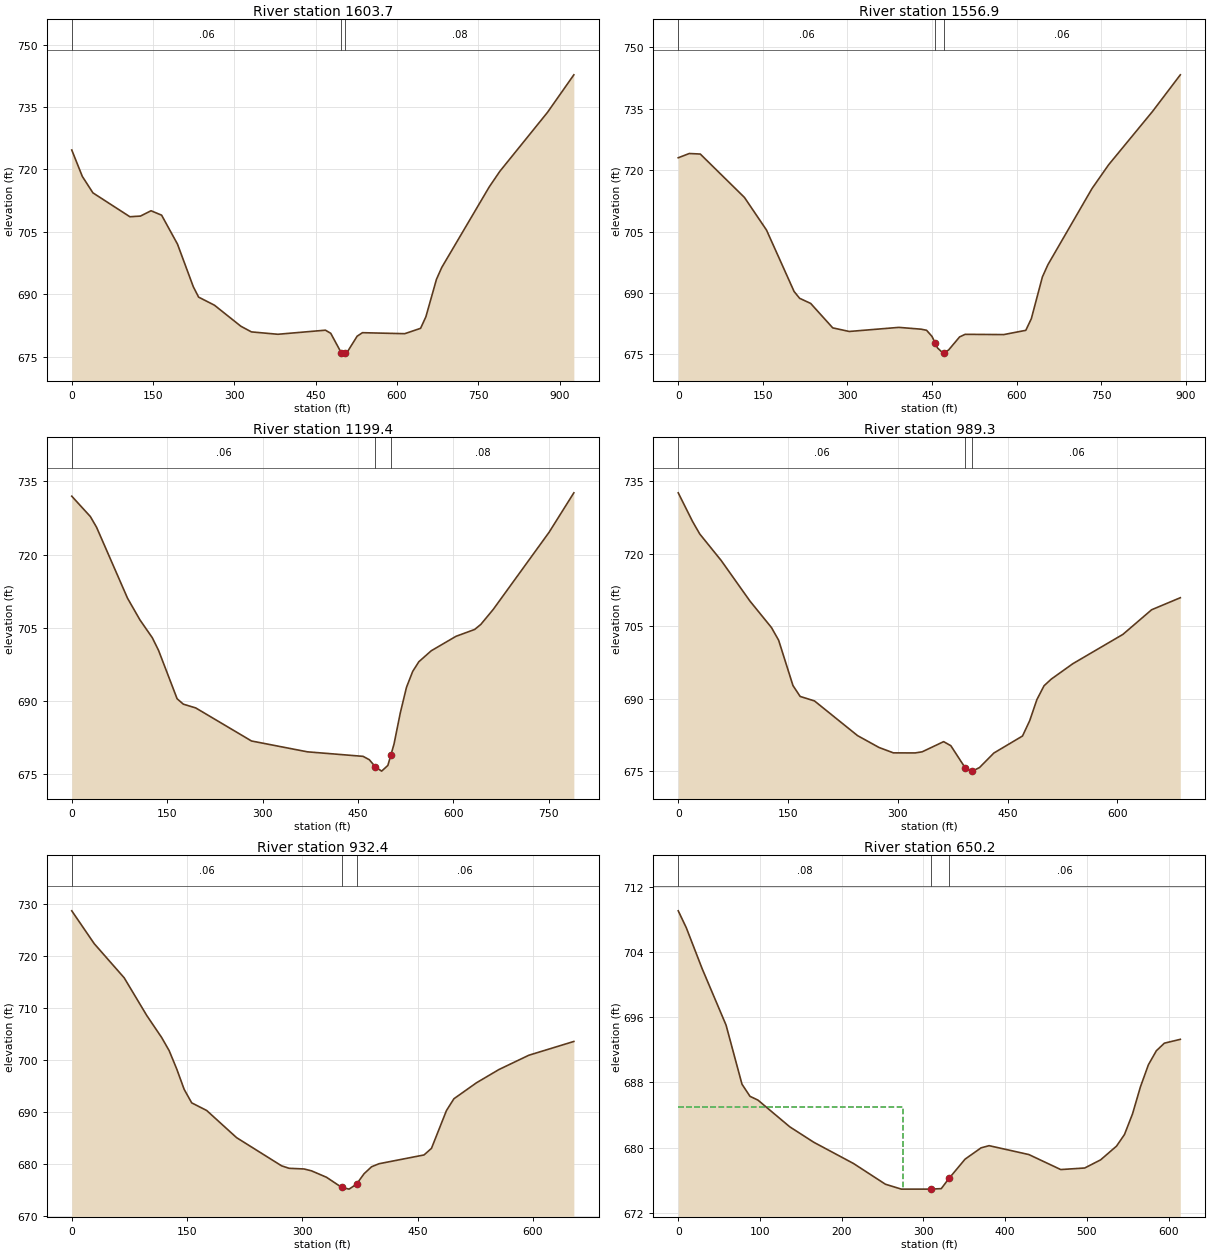
Type RM Length L Ch R = 1 ,1603.7  ,47.5,46.8,46.9
XS GIS Cut Line= 2
      1844658.36      691550.476      1844985.16      690683.928
#Sta/Elev= 30
       0  724.68    19.5  718.33      39  714.39   107.2  708.65   126.7  708.81
   146.2  710.09   165.7  709.03     195  702.08   224.2  691.83     234  689.34
   263.2   687.4     312  682.34   331.4  680.99   380.2  680.42   467.9   681.4
   477.7  680.65   497.2  675.95   504.6   675.9   506.9  675.89   526.4  679.96
   536.2   680.8   614.2  680.56   643.4  681.85   653.2  684.63   672.7  693.62
   682.4  696.46   770.1  715.83   789.6  719.56   877.4  733.71   926.1  742.74
#Mann= 3 , 0 , 0
       0     .06       0   497.2    .045       0   504.6     .08       0
Bank Sta=497.2,504.6
XS Rating Curve= 0 ,0
Exp/Cntr=0.3,0.1

Type RM Length L Ch R = 1 ,1556.9  ,359,357.5,355.9
XS GIS Cut Line= 2
     1844727.937       691544.15     1845012.569      690700.795
#Sta/Elev= 30
       0  723.03    19.6  724.07    39.1  723.94   117.4  713.34   156.5  705.37
   205.4  690.37   215.2   688.7   234.8  687.45   273.9  681.48   303.2   680.6
   391.2   681.6   430.4  681.16   440.2   680.9   449.9  679.39   455.8  677.69
   459.7  676.57   469.5  675.31   470.8  675.41   479.3  676.07   498.8  679.27
   508.6   679.9   577.1  679.84   616.2  680.88     626  683.73   645.6  693.92
   655.3  696.89   733.6  715.52   762.9   721.3   841.2  734.41   890.1  743.29
#Mann= 3 , 0 , 0
       0     .06       0   455.8    .045       0   470.8     .06       0
Bank Sta=455.8,470.8
XS Rating Curve= 0 ,0
Exp/Cntr=0.3,0.1

Type RM Length L Ch R = 1 ,1199.4  ,208.3,210.1,211.7
XS GIS Cut Line= 2
     1845038.278      691544.908     1845229.734      690778.805
#Sta/Elev= 30
       0  731.97    29.2   727.8      39   725.6    87.7  711.05   107.2  706.61
   126.7  702.94   136.5  700.35   165.7  690.43   175.5  689.32     195  688.55
   282.7  681.77   370.5  679.55   458.2  678.62     468  677.93   477.7  676.44
   487.4  675.59   497.2  676.76   501.9  678.89   506.9  681.16   516.7  687.51
   526.4  692.75   536.2  696.03   545.9  698.02   565.4  700.27   604.4  703.24
   633.7  704.64   643.4  705.68   662.9  708.75   750.7  724.56   789.7  732.66
#Mann= 3 , 0 , 0
       0     .06       0   477.7    .045       0   501.9     .08       0
Bank Sta=477.7,501.9
XS Rating Curve= 0 ,0
Exp/Cntr=0.3,0.1

Type RM Length L Ch R = 1 ,989.3   ,58,56.9,55.8
XS GIS Cut Line= 2
     1845214.975      691550.476     1845423.705      690896.875
#Sta/Elev= 30
       0  732.61    19.6  726.68    29.4   724.1    58.8  718.59      98  710.22
   127.4  704.74   137.2  702.12   156.8  692.74   166.6  690.49   186.2  689.56
     245  682.39   274.4  679.93     294  678.82   323.5   678.8   333.3  679.03
   362.7  681.14   372.5   680.3   392.1  675.73   401.9  675.04   411.7  675.78
   431.3  678.78   470.5  682.31   480.3  685.48   490.1  689.83   499.9   692.7
   509.7  694.07   539.1  697.25   607.7  703.33   646.9  708.42   686.1  710.91
#Mann= 3 , 0 , 0
       0     .06       0   392.1    .045       0   401.9     .06       0
Bank Sta=392.1,401.9
XS Rating Curve= 0 ,0
Exp/Cntr=0.3,0.1

Type RM Length L Ch R = 1 ,932.4   ,294,282.3,270.6
XS GIS Cut Line= 2
     1845278.226      691550.476     1845463.765      690924.284
#Sta/Elev= 30
       0  728.72    29.2   722.4    68.2  715.82    97.5  708.58     117  704.31
   126.7   701.8   136.5  698.28   146.2  694.35     156  691.75   175.5  690.28
   214.4  685.05   272.9  679.63   282.7  679.15   302.2  679.02   311.9  678.66
   331.4  677.42   350.9   675.5   360.7  675.14   370.4  676.09   380.2   678.1
   389.9  679.44   399.7  680.03   458.2  681.72   467.9  682.99   487.4  690.27
   497.1  692.54   526.4  695.61   555.6  698.16   594.6  700.92   653.1  703.57
#Mann= 3 , 0 , 0
       0     .06       0   350.9    .045       0   370.4     .06       0
Bank Sta=350.9,370.4
XS Rating Curve= 0 ,0
Exp/Cntr=0.3,0.1

Type RM Length L Ch R = 1 ,650.2   ,647.2,650.2,652.2
XS GIS Cut Line= 2
     1845714.663      691548.367     1845552.317       690955.91
#Sta/Elev= 30
       0  709.03     9.8  706.97    29.2  701.95    58.5  695.02      78  687.77
    87.8  686.28    97.5  685.82   136.5  682.54   165.8  680.65   214.5  678.04
   253.5   675.5     273   674.9   308.7   674.9   321.8  674.96   331.5  676.24
     351  678.58   370.5  679.96   380.3  680.23     429  679.14     468   677.3
   497.3  677.49   516.8  678.49   536.3  680.18     546   681.6   555.8  684.12
   565.5  687.44   575.3  690.16     585  691.87   594.8   692.8   614.3  693.27
#Mann= 3 , 0 , 0
       0     .08       0   308.7    .045       0   331.5     .06       0
#XS Ineff= 2 , 0
       0     275     685               0
Permanent Ineff=
       F       F
Bank Sta=308.7,331.5
XS Rating Curve= 0 ,0
Exp/Cntr=0.3,0.1

Chan Stop Cuts=-1
Use User Specified Reach Order=0
Composite Channel Slope=5